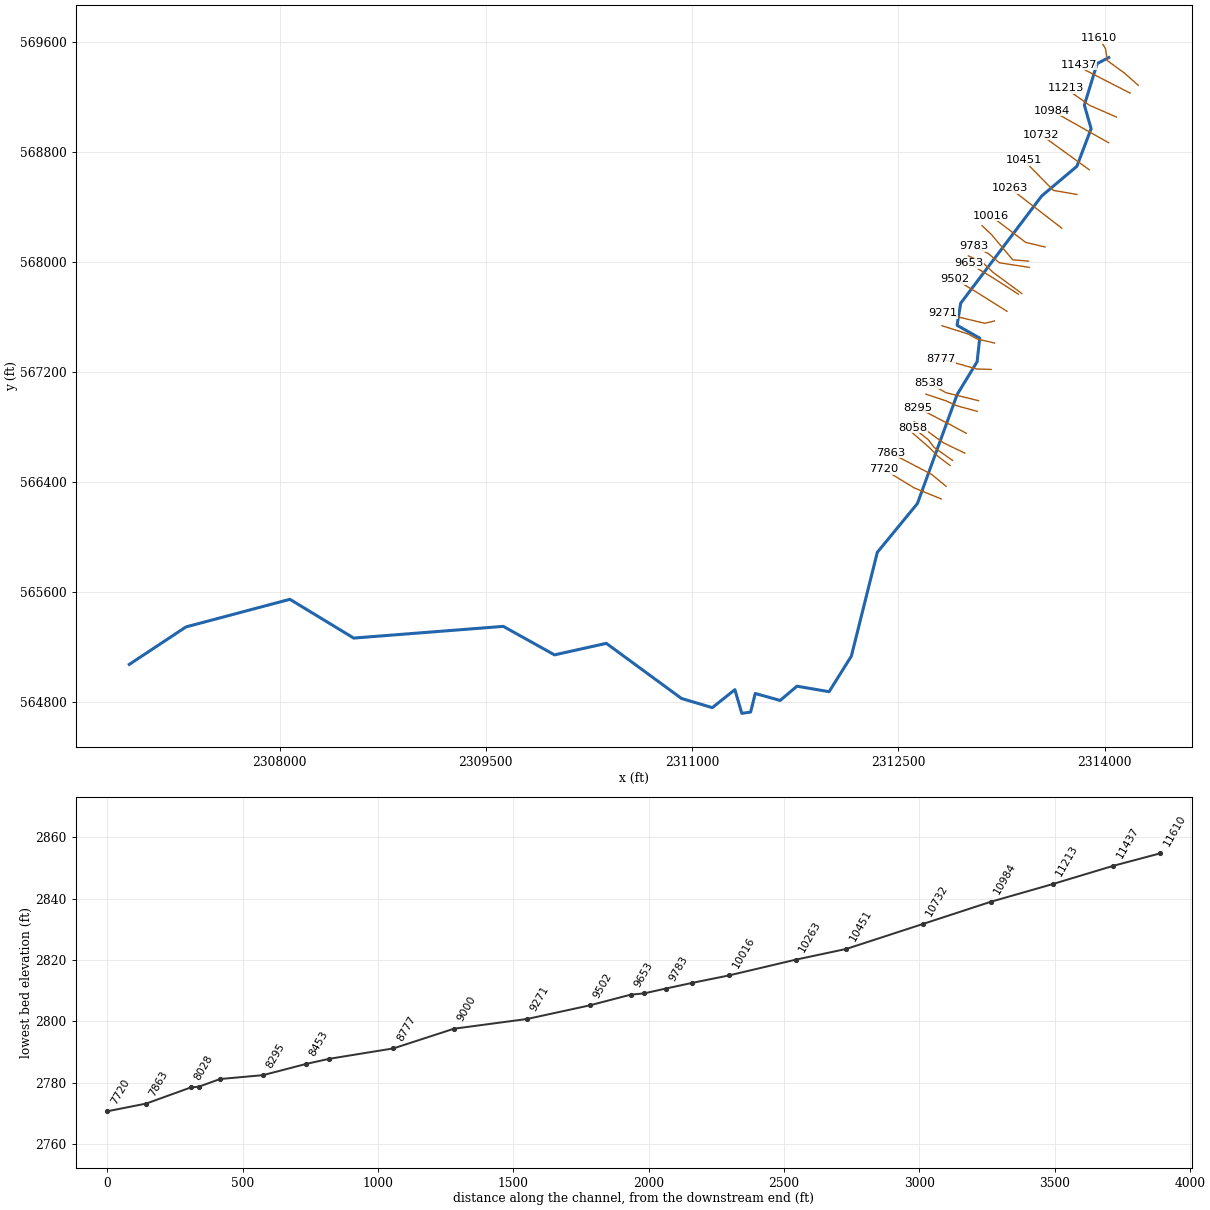
--- JHNSRN.prj (project) ---

Proj Title=JHNSRN
Current Plan=p01
Default Exp/Contr=0,0
English Units
Geom File=g01
Flow File=f01
Plan File=p01
Background Map Layer=Inundation Boundary (01pct Value_0)
Background Map Layer=Inundation Boundary (01pct Value_0)
Background Map Layer=Inundation Boundary (01pct Value_0)
BEGIN DESCRIPTION:
----------MODEL BY WOOD PLC 2021----------
Stream Name: Johns Run
Flood Zone: Enhanced Approximate
Pocahontas County, WV
HEC-RAS Version: RAS 6.1
Vertical Datum: NAVD88
Projection: NAD 1983 StatePlane West Virginia S FIPS 4702 (US Feet)
Terrain: 1-meter LIDAR (FEMA Region III 3DEP collected 2016-2018)
Land Use: 2019 NLCD
Hydrologic Method:
WV SIR2010-5033 regression equations
Model Notes:
END DESCRIPTION:
DSS File=dss
DSS Export Rating Curves= 0
DSS Export Rating Curve Sorted= 0
DSS Export Volume Flow Curves= 0
DXF OffsetX= 0
DXF OffsetY= 0
DXF ScaleX= 0
DXF ScaleY= 0

--- JHNSRN.p01 (plan) ---

Plan Title=Floodplain
Program Version=6.10
Short Identifier=Floodplain
Geom File=g01
Flow File=f01
Subcritical Flow
K Sum by GR= 0
Std Step Tol= 0.01
Critical Tol= 0.01
Num of Std Step Trials= 20
Max Error Tol= 0.3
Flow Tol Ratio= 0.001
Split Flow NTrial= 30
Split Flow Tol= 0.02
Split Flow Ratio= 0.02
Log Output Level= 0
Friction Slope Method= 1
Unsteady Friction Slope Method= 2
Unsteady Bridges Friction Slope Method= 1
Parabolic Critical Depth
Global Vel Dist= 0 , 0 , 0
Global Log Level= 0
CheckData=True
Encroach Param=-1 ,0,0, 0
Computation Interval=0.1SEC
Output Interval=1SEC
Instantaneous Interval=Max Profile
Mapping Interval=1HOUR
Computation Time Step Use Courant=        0
Computation Time Step Use Time Series=    0
Computation Time Step Count To Double=0
Computation Time Step Max Doubling=0
Computation Time Step Max Halving=0
Computation Time Step Residence Courant=0
Run HTab= 0
Run UNet= 0
Run Sediment= 0
Run PostProcess= 0
Run WQNet= 0
Run RASMapper=-1
UNET Theta= 0
UNET Theta Warmup= 0
UNET ZTol= 0
UNET ZSATol= 0
UNET MxIter= 0
UNET Max Iter WO Improvement= 0
UNET MaxInSteps= 0
UNET DtIC= 0
UNET DtMin= 0
UNET MaxCRTS= 0
UNET WFStab= 0
UNET SFStab= 0
UNET WFX= 1
UNET SFX= 1
UNET Gravity=32.174
UNET 1D Methodology=Finite Difference
UNET DSS MLevel= 1
UNET Pardiso=0
UNET DZMax Abort= 0
UNET Use Existing IB Tables= 0
UNET Froude Reduction=False
UNET Froude Limit= 0
UNET Froude Power= 0
UNET D1 Cores= 0
UNET WindReference=Eulerian
UNET WindDragFormulation=Hsu (1988)
UNET D2 Coriolis=0
UNET D2 Cores= 0
UNET D2 Theta= 1
UNET D2 Theta Warmup= 1
UNET D2 Z Tol= 0.01
UNET D2 Volume Tol= 0.01
UNET D2 Max Iterations= 20
UNET D2 Equation= 0
UNET D2 RampUpFraction=0.1
UNET D2 TimeSlices= 1
UNET D2 Turbulence Formulation=Non-Conservative (original)
UNET D2 Eddy Viscosity=0.3
UNET D2 Transverse Eddy Viscosity=0.1
UNET D2 Smagorinsky Mixing=0
UNET D2 BCVolumeCheck=0
UNET D2 Cores=0
UNET D2 SolverType=PARDISO (Direct)
UNET D2 Minimum Iterations= 2147483647
UNET D2 Maximum Iterations= 2147483647
UNET D2 Restart Number= 10
UNET D2 Relaxation Coeff=1.3
UNET D2 SOR Precondition Iterations= 10
UNET D2 ILUT Maximum Fill= 8
UNET D2 ILUT Tolerance=1E-08
UNET D1D2 MaxIter= 0
UNET D1D2 ZTol=0.01
UNET D1D2 QTol=0.1
UNET D1D2 MinQTol=1
DSS File=dss
Write IC File= 0
Write IC File at Fixed DateTime=0
Write IC File at Sim End=0
Echo Input=False
Echo Parameters=False
Echo Output=False
Write Detailed= 0
HDF Write Warmup=0
HDF Write Time Slices=0
HDF Flush=0
HDF Compression= 1
HDF Chunk Size= 1
HDF Spatial Parts= 1
HDF Use Max Rows=0
HDF Fixed Rows= 1
Calibration Method= 0
Calibration Iterations= 20
Calibration Max Change=0.05
Calibration Tolerance=0.2
Calibration Maximum=1.5
Calibration Minimum=0.5
Calibration Optimization Method= 1
WQ AD Non Conservative
WQ ULTIMATE=-1
WQ Max Comp Step=1HOUR
WQ Output Interval=15MIN
WQ Output Selected Increments= 0
WQ Output face flow=0
WQ Output face velocity=0
WQ Output face area=0
WQ Output face dispersion=0
WQ Output cell volume=0
WQ Output cell surface area=0
WQ Output cell continuity=0
WQ Output cumulative cell continuity=0
WQ Output face conc=0
WQ Output face dconc_dx=0
WQ Output face courant=0
WQ Output face peclet=0
WQ Output face adv mass=0
WQ Output face disp mass=0
WQ Output cell mass=0
WQ Output cell source sink temp=0
WQ Output nsm pathways=0
WQ Output nsm derived pathways=0
WQ Create Restart=0
WQ Fixed Restart=0
WQ System Summary=0
WQ Write To DSS=0
Sorting and Armoring Iterations= 10
XS Update Threshold= 0.02
Bed Roughness Predictor= 0
Hydraulics Update Threshold= 0.02
Energy Slope Method= 1
Volume Change Method= 1
Sediment Retention Method= 0
Sediment TS Multiplier= 1
Warm Up Method= 0
XS Weighting Method= 0
Number of US Weighted Cross Sections= 1
Number of DS Weighted Cross Sections= 1
Upstream XS Weight=0
Main XS Weight=1
Downstream XS Weight=0
Number of DS XS's Weighted with US Boundary= 1
Upstream Boundary Weight= 1
Weight of XSs Associated with US Boundary= 0
Number of US XS's Weighted with DS Boundary= 1
Downstream Boundary Weight= 0.5
Weight of XSs Associated with DS Boundary= 0.5
Percentile Method= 0
Sediment Output Level= 3
Mass or Volume Output= 0
Output Increment Type= 1
Profile and TS Output Increment= 1
Transport Output Increment 1
XS Output Flag= 0
XS Output Increment= 10
Read HDF5 Sediment Hotstart= 0
Sediment Hotstart Type= 0
Write Gradation File= 0
Read Gradation Hotstart= 0
Write HDF5 File= 1
Write Binary Output= 1
Write DSS Sediment File= 0
DSS Sediment Output Type= 1
SV Curve= 0
Specific Gage Flag= 0
Subcell Erosion Methods= 0
Subcell Deposition Methods= 0
Advection Scheme= 1
Matrix Solver= 0
Implicit Weighting Factor= 1
Maximum Outer Loop Convergence Iterations= 5
Convergence Maximum Absolute= 0.001
Convergence RMSE= 0.0001
Grain Fractions Max Abs Error= 0.001
Max Subgrid Regions= 1
Max Subgrid Length Scale= 3.402823E+38
Initial Layer Thickness= 3.402823E+38
Min Layer Thickness= 3.402823E+38
Max Layer Thickness= 3.402823E+38
Number of Layers= 5

--- JHNSRN.f01 (steady flow) ---

Flow Title=Flow
Program Version=6.10
Number of Profiles= 6
Profile Names=01pct,10pct,04pct,02pct,0_2pct,01plus
River Rch & RM=JHNSRN,Main            ,11610
     644     342     453     545     897     952
River Rch & RM=JHNSRN,Main            ,5365
     855     459     606     727    1190    1260
Boundary for River Rch & Prof#=JHNSRN,Main            , 1
Up Type= 0
Dn Type= 3
Dn Slope=0.00534
Boundary for River Rch & Prof#=JHNSRN,Main            , 2
Up Type= 0
Dn Type= 3
Dn Slope=0.00534
Boundary for River Rch & Prof#=JHNSRN,Main            , 3
Up Type= 0
Dn Type= 3
Dn Slope=0.00534
Boundary for River Rch & Prof#=JHNSRN,Main            , 4
Up Type= 0
Dn Type= 3
Dn Slope=0.00534
Boundary for River Rch & Prof#=JHNSRN,Main            , 5
Up Type= 0
Dn Type= 3
Dn Slope=0.00534
Boundary for River Rch & Prof#=JHNSRN,Main            , 6
Up Type= 0
Dn Type= 3
Dn Slope=0.00534
DSS Import GetInterval= 0
DSS Import GetPeak= 0
DSS Import FillOption= 0

--- JHNSRN.g01 (geometry) ---

Geom Title=Geometry
Program Version=6.10

River Reach=JHNSRN          ,Main
Reach XY= 30
     2314028.839      569485.5132313944.36775056569441.937652277
2313851.67048885569140.0452188822313900.81860371568968.766218661
2313797.26490595568694.849985872     2313541.317      568479.049
     2312952.441      567698.9672312926.05823721567538.641080099
      2313090.89      567445.2762313071.89835955567273.689238764
     2312926.193      567034.1482312638.06142997566242.799135096
     2312346.094      565887.268     2312157.445      565132.398
2311995.65571833564873.934733181     2311761.898      564913.701
2311639.59607224564810.2274940992311458.64851206564860.791345027
2311425.10981887564725.650118218     2311360.998      564716.154
2311310.61299526564888.587905668     2311146.304      564757.819
2310922.12095245564824.744900448     2310375.761      565225.537
2309999.01951085565141.7142929192309626.71060474565348.963511073
     2308538.991      565263.768     2308075.048      565545.745
     2307319.521      565344.874     2306907.334      565072.384

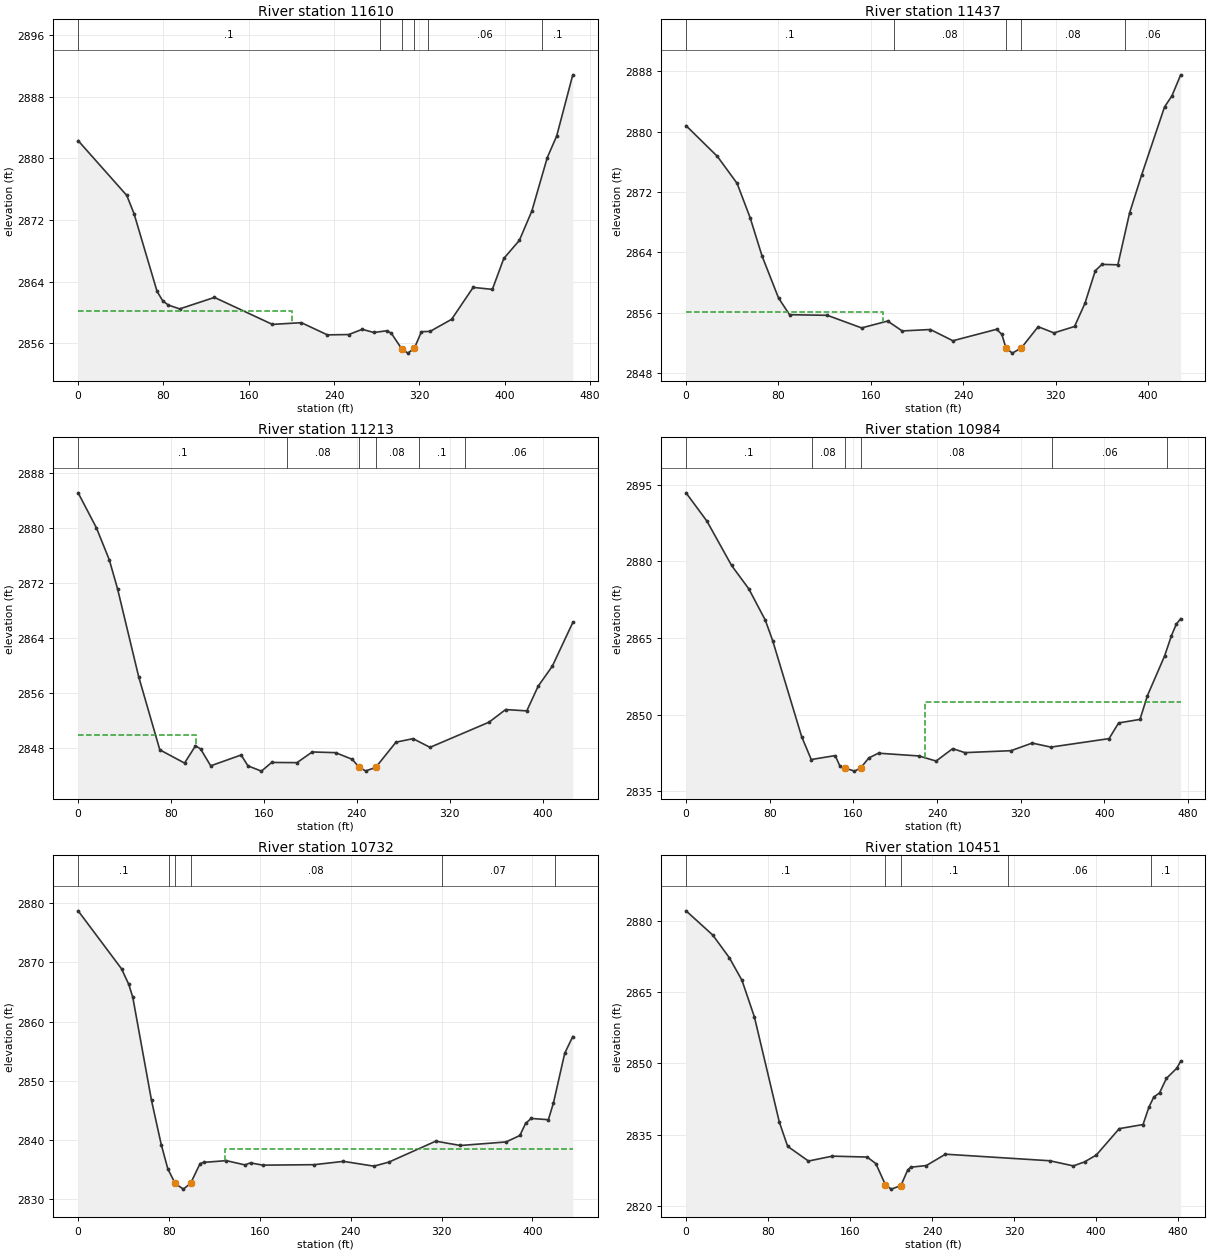
Type RM Length L Ch R = 1 ,11610   ,173.1,173.1,173.1
XS GIS Cut Line= 5
2314243.37591092569283.9398730822314143.97801747569372.184324509
     2314018.841569463.4955708172314005.84751474569549.712525676
2313959.87335894 569625.63733308
#Sta/Elev= 30
       0 2882.28    45.6 2875.17    52.4 2872.81      74 2862.72    79.2 2861.52
    84.5 2860.95    95.2 2860.45   127.8 2861.94   182.1 2858.44   209.3 2858.66
   233.7 2857.08   253.7 2857.12   266.4  2857.8   277.1 2857.39   289.5 2857.61
   293.6  2857.3   303.52855.251   309.2 2854.71   315.2 2855.33   321.9 2857.49
     330 2857.53   350.2  2859.1   370.4 2863.24   388.4 2862.98   399.1 2866.99
   413.7 2869.34   425.4 2873.14   439.9 2880.09   448.7 2882.88   463.8 2890.82
#Mann= 6 ,-1,0
       0      .1       0  282.92     .08       0   303.5    .045       0
   315.2     .08       0  327.83     .06       0  435.02      .1       0
#XS Ineff= 2 , 0
           200.6 2860.14
Permanent Ineff=
       F       F
Bank Sta=303.5,315.2
XS Rating Curve= 0 ,0
Exp/Cntr=0.3,0.1

Type RM Length L Ch R = 1 ,11437   ,225,224.1,220.7
XS GIS Cut Line= 3
2314183.49672899569227.8811506412313863.15565836569391.943680267
 2313809.2665063569433.857465209
#Sta/Elev= 30
       0  2880.8    27.2 2876.71    44.2 2873.15    55.5 2868.59    65.8 2863.53
    80.1 2857.95    89.6 2855.75   122.3 2855.67     152    2854   174.5 2854.91
   187.1  2853.6   211.5 2853.79     231  2852.3   268.9 2853.82   273.4 2853.14
   276.9 2851.36   282.4 2850.66   290.2 2851.34   304.8 2854.16   318.5 2853.34
   336.3 2854.19   345.3 2857.25   354.3 2861.59   360.1 2862.42   373.8 2862.36
     384 2869.25   394.5 2874.31   414.2 2883.27   420.6 2884.74   428.2 2887.53
#Mann= 5 ,-1,0
       0      .1       0     180     .08       0   276.9    .045       0
   290.2     .08       0  379.91     .06       0
#XS Ineff= 2 , 0
          170.15 2856.16
Permanent Ineff=
       F       F
Bank Sta=276.9,290.2
XS Rating Curve= 0 ,0
Exp/Cntr(USF)=0,0
Exp/Cntr=0.3,0.1

Type RM Length L Ch R = 1 ,11213   ,229,228.8,231
XS GIS Cut Line= 3
 2314084.6999502569053.0407906012313889.50146604569138.664665552
2313715.85864271569261.412178594
#Sta/Elev= 30
       0 2885.08    15.7 2880.01    26.8 2875.37    33.9 2871.17    52.1 2858.41
    70.3  2847.8    91.6 2845.88     101 2848.38   105.4 2847.93   114.1 2845.48
   140.3 2847.05   146.2 2845.47   157.8 2844.71   166.6 2845.97   188.4 2845.94
   201.5 2847.49   221.6 2847.39     236 2846.42   241.7 2845.29   247.5 2844.74
   256.1 2845.24   273.6 2848.91   288.3 2849.42   302.9 2848.16   353.7 2851.81
     368 2853.64   386.2 2853.45     396 2857.03   408.2 2859.94   425.8 2866.27
#Mann= 6 ,-1,0
       0      .1       0     180     .08       0   241.7    .045       0
   256.1     .08       0  293.15      .1       0  333.15     .06       0
#XS Ineff= 2 , 0
          101.59 2849.91
Permanent Ineff=
       F       F
Bank Sta=241.7,256.1
XS Rating Curve= 0 ,0
Exp/Cntr(USF)=0,0
Exp/Cntr=0.3,0.1

Type RM Length L Ch R = 1 ,10984   ,249.5,251.6,248.1
XS GIS Cut Line= 2
 2314028.4157247568866.2250634352313616.46309557 569098.54718568
#Sta/Elev= 30
       0 2893.39      20 2887.84    43.5 2879.19      60  2874.6    75.8 2868.47
    82.9 2864.42   110.5  2845.7   119.7 2841.21   142.6 2841.98   147.2 2839.88
   151.8 2839.57     161 2838.94   166.8 2839.53   174.8 2841.53     184 2842.45
   222.6 2841.91   239.1 2840.91   254.9 2843.34   266.6 2842.56   310.7 2842.94
   330.9 2844.43   348.8 2843.64   404.4  2845.3   413.6 2848.37     434 2849.06
   441.1 2853.71   457.5 2861.46   464.1 2865.46   468.7  2867.7   472.9 2868.77
#Mann= 6 ,-1,0
       0      .1       0     120     .08       0   151.8    .045       0
   166.8     .08       0     350     .06       0     460      .1       0
#XS Ineff= 2 , 0
                          228.41         2852.54
Permanent Ineff=
       F       F
Bank Sta=151.8,166.8
XS Rating Curve= 0 ,0
Exp/Cntr(USF)=0,0
Exp/Cntr=0.3,0.1

Type RM Length L Ch R = 1 ,10732   ,283.2,281.7,279.6
XS GIS Cut Line= 2
2313887.10639262568669.8290425682313534.43183076568925.503130709
#Sta/Elev= 30
       0  2878.7    38.2 2868.91    44.6 2866.27    48.1 2864.11    64.6 2846.68
    73.2  2839.2      79  2835.1    85.42832.666    92.6 2831.69      99 2832.66
   107.4 2836.01   110.5 2836.21   130.5  2836.5   146.9 2835.78   151.8 2836.13
   162.5 2835.74   207.9 2835.82   233.6 2836.38   260.5 2835.57   273.7 2836.26
   314.9 2839.79   336.7 2839.06   376.8 2839.66     389 2840.75     394 2842.78
   398.9 2843.63   414.1 2843.42   418.6 2846.27   428.5 2854.64   435.6 2857.47
#Mann= 6 ,-1,0
       0      .1       0      80     .08       0    85.4    .045       0
      99     .08       0     320     .07       0     420     .06       0
#XS Ineff= 2 , 0
                          129.61         2838.52
Permanent Ineff=
       F       F
Bank Sta=85.4,99
XS Rating Curve= 0 ,0
Exp/Cntr(USF)=0,0
Exp/Cntr=0.3,0.1

Type RM Length L Ch R = 1 ,10451   ,185.5,187.6,188.9
XS GIS Cut Line= 3
2313797.88990753568490.1985356782313626.77521726568519.538185137
  2313410.486781568739.884940256
#Sta/Elev= 30
       0 2882.07    26.1 2876.97    42.2 2872.22    54.5 2867.49    66.7 2859.75
      91 2837.66    99.1 2832.59   119.4  2829.5   142.6 2830.53   176.6 2830.34
   185.1 2828.97   194.5 2824.48   200.2  2823.6   209.5 2824.34   216.2 2827.62
     219  2828.2   234.4 2828.56     253 2830.94   354.8 2829.56   377.7 2828.48
   388.6 2829.32   400.1 2830.76   422.5 2836.31   445.7 2837.17   451.4 2840.82
   456.2 2842.95   461.8 2843.83   468.5 2846.87   478.6 2849.01   482.4 2850.47
#Mann= 5 ,-1,0
       0      .1       0   194.5    .045       0   209.5      .1       0
  313.61     .06       0  453.61      .1       0
Bank Sta=194.5,209.5
XS Rating Curve= 0 ,0
Exp/Cntr(USF)=0,0
Exp/Cntr=0.3,0.1

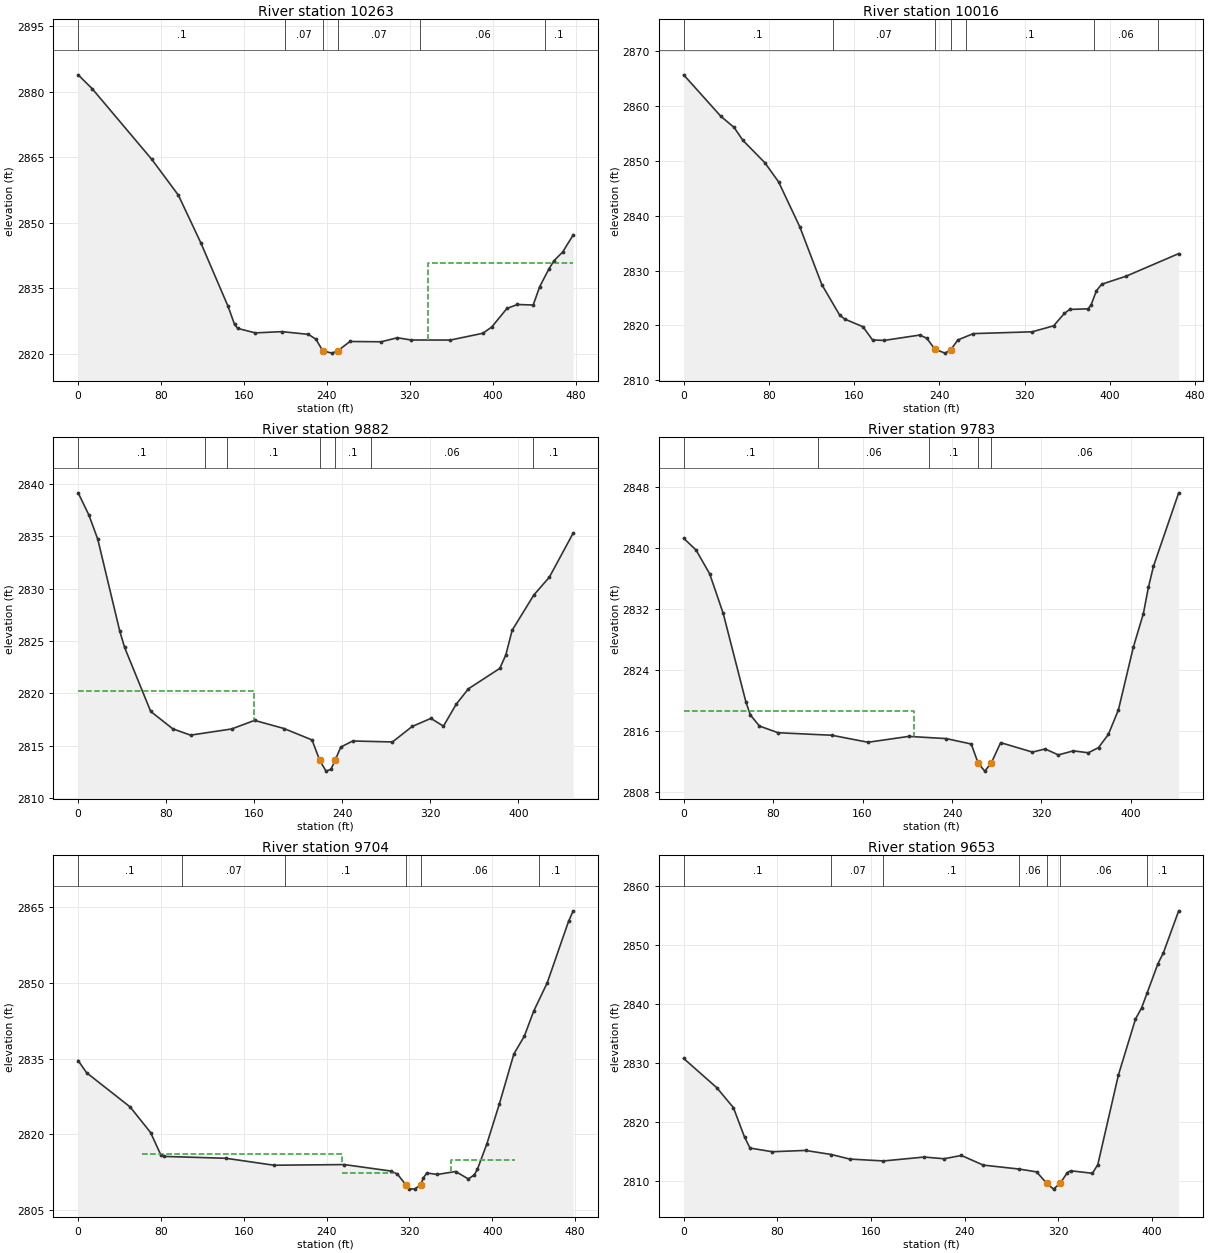
Type RM Length L Ch R = 1 ,10263   ,246.3,246.7,246.3
XS GIS Cut Line= 2
2313687.51694052568244.8365692292313309.62757787 568536.90246747
#Sta/Elev= 30
       0 2883.89    13.6 2880.69    71.1 2864.49    96.7 2856.29   118.3 2845.39
   144.5 2830.88   150.9 2826.67   153.8 2825.77   170.9 2824.73   196.5 2825.02
   222.2 2824.39   229.5 2823.25     236 2820.59     245 2820.09   250.7 2820.66
   262.2 2822.76   292.4 2822.69     308 2823.62   321.1  2823.1   359.1 2823.09
   390.4 2824.64     399 2826.08   413.7 2830.34   423.8 2831.24     439 2831.12
   445.3 2835.34   454.2 2839.41   459.2 2841.31   467.4 2843.26   477.6 2847.19
#Mann= 6 ,-1,0
       0      .1       0     200     .07       0     236    .045       0
   250.7     .07       0     330     .06       0     450      .1       0
#XS Ineff= 2 , 0
                          337.21         2840.83
Permanent Ineff=
       F       F
Bank Sta=236,250.7
XS Rating Curve= 0 ,0
Exp/Cntr(USF)=0,0
Exp/Cntr=0.3,0.1

Type RM Length L Ch R = 1 ,10016   ,137.2,134.6,132
XS GIS Cut Line= 3
2313566.25692031568107.8615575692313425.22842118568141.685465897
2313170.68917885568334.883043971
#Sta/Elev= 30
       0 2865.72      35 2858.14    47.4 2856.12    55.6 2853.77    76.2 2849.69
    89.1  2846.2   109.1 2837.96   129.7 2827.45   146.4 2821.91   151.1 2821.18
   168.3 2819.77   177.3 2817.36   188.2 2817.28   221.7 2818.26   228.2 2817.67
   235.82815.681   245.3 2814.96   250.72815.568   257.3 2817.36   271.9 2818.52
   327.1 2818.85   347.2 2819.94   357.3  2822.2   362.3 2822.93   379.5 2823.04
   382.4 2823.75   387.4 2826.35   392.4 2827.53   415.5 2829.01   464.6 2833.11
#Mann= 7 ,-1,0
       0      .1       0     140     .07       0   235.8    .045       0
   250.7     .07       0  265.03      .1       0  385.03     .06       0
  445.03      .1       0
Bank Sta=235.8,250.7
XS Rating Curve= 0 ,0
Exp/Cntr(USF)=0,0
Exp/Cntr=0.3,0.1

Type RM Length L Ch R = 1 ,9882    ,96.5,99,100.7
XS GIS Cut Line= 4
2313445.86673813568005.2432594232313330.63613518568014.989131314
2313177.56861784568197.2942643332313107.62765485568263.222221243
#Sta/Elev= 30
       0 2839.16     9.7 2837.05    17.8 2834.73    37.8 2825.94    42.2 2824.38
    65.9 2818.27      86  2816.6   102.1    2816   139.4 2816.59   160.3 2817.41
   187.1 2816.63   212.5 2815.54  219.52 2813.58   225.2 2812.56   229.7 2812.74
   233.4 2813.58   238.6 2814.86   249.5 2815.44   285.6 2815.35   303.5 2816.83
   320.5  2817.6   331.9 2816.86   343.4 2818.94   354.6 2820.43   383.1 2822.38
   388.6 2823.67   394.3 2826.02     414 2829.39   428.2 2831.11   449.8 2835.32
#Mann= 7 ,-1,0
       0      .1       0  115.64     .06       0  135.64      .1       0
  219.52    .045       0   233.4      .1       0  265.64     .06       0
  413.69      .1       0
#XS Ineff= 2 , 0
             160 2820.25
Permanent Ineff=
       F       F
Bank Sta=219.52,233.4
XS Rating Curve= 0 ,0
Exp/Cntr(USF)=0,0
Exp/Cntr=0.3,0.1

Type RM Length L Ch R = 1 ,9783    ,79.8,79.2,78.3
BEGIN DESCRIPTION:
structure xs 4
END DESCRIPTION:
XS GIS Cut Line= 4
2313451.18839267567959.8274887172313234.30118805  567993.0923974
2313152.46951269568060.9528111152313048.01769943568113.511366834
#Sta/Elev= 30
       0 2841.26    11.1 2839.71    23.3 2836.58    35.4 2831.38    55.7 2819.75
    59.7 2818.05    67.8  2816.6    84.5 2815.72   132.5 2815.39   164.9 2814.47
   201.3 2815.24   234.9 2814.95   257.2 2814.24   263.4 2811.71   269.3 2810.68
     275 2811.72   283.5 2814.42   311.9 2813.18   323.3 2813.59   335.1 2812.81
   348.5 2813.34   361.9 2813.09     371 2813.77   379.8  2815.5   388.8 2818.72
   402.2 2826.98   411.1 2831.35   415.6 2834.79   420.1 2837.55   442.7 2847.22
#Mann= 5 ,-1,0
       0      .1       0     120     .06       0  219.42      .1       0
   263.4    .045       0     275     .06       0
#XS Ineff= 2 , 0
           206.2 2818.54
Permanent Ineff=
       F       F
Bank Sta=263.4,275
XS Rating Curve= 0 ,0
Exp/Cntr(USF)=0,0
Exp/Cntr=0.5,0.3

Type RM Length L Ch R = 1 ,9704    ,47.9,50,52.5
BEGIN DESCRIPTION:
structure xs 3
END DESCRIPTION:
XS GIS Cut Line= 4
2313396.63394243567770.2175092222313189.06091225567922.570790992
2313111.22102593567996.4188882692313008.09980901568043.655058599
#Sta/Elev= 30
       0 2834.62     8.2  2832.2    50.2 2825.43      70 2820.34    79.7 2815.98
    82.6 2815.62   142.7 2815.25   189.1 2813.87   257.1    2814     302 2812.72
   308.3 2812.13   316.5    2810   319.4 2809.22   324.9 2809.13   330.7 2809.96
   333.5 2811.38   336.8 2812.33   346.9 2812.04   364.6 2812.62   376.9 2811.16
   382.7 2811.95   385.7 2813.09   394.8 2818.11   406.9 2826.05   420.9 2835.94
     431 2839.47   440.1 2844.46   453.1 2850.04   473.7 2862.24   478.2 2864.32
#Mann= 6 ,-1,0
       0      .1       0     100     .07       0     200      .1       0
   316.5    .045       0   330.7     .06       0  444.78      .1       0
#XS Ineff= 4 ,-1
   61.77  254.772816.164  254.77   306.5  2812.3   340.7  360.38 2811.91
  360.38  422.04 2814.81
Permanent Ineff=
       F       F       F       F
Bank Sta=316.5,330.7
XS Rating Curve= 0 ,0
Exp/Cntr(USF)=0,0
Exp/Cntr=0.5,0.3

Type RM Length L Ch R = 1 ,9653    ,151.8,151.7,151.6
BEGIN DESCRIPTION:
structure xs 2
END DESCRIPTION:
XS GIS Cut Line= 3
2313371.91276907567765.0361816392313173.55561176567892.305802803
2313013.03536885 567988.61794855
#Sta/Elev= 30
       0 2830.82    28.2 2825.89    42.5  2822.5      52 2817.52    56.7 2815.65
    75.7 2815.03   104.1 2815.25   126.2 2814.56   141.8 2813.79   170.7 2813.47
   205.5 2814.13   222.5 2813.84   237.3  2814.4   255.9 2812.77   286.9 2812.09
   301.5 2811.62   310.2 2809.68     316  2808.7   321.9 2809.76   327.7 2811.47
   330.6 2811.81   349.2 2811.38   353.8 2812.84   371.4 2828.01     386 2837.49
   391.2 2839.36   395.9 2841.88   405.2 2846.86   409.9 2848.73   422.9  2855.8
#Mann= 7 ,-1,0
       0      .1       0   126.2     .07       0   170.7      .1       0
   286.9     .06       0   310.2    .045       0   321.9     .06       0
   395.9      .1       0
#XS Ineff= 2 , 0
             304    2810     328            2810
Permanent Ineff=
       F       F
Bank Sta=310.2,321.9
XS Rating Curve= 0 ,0
Exp/Cntr(USF)=0,0
Exp/Cntr=0.5,0.3

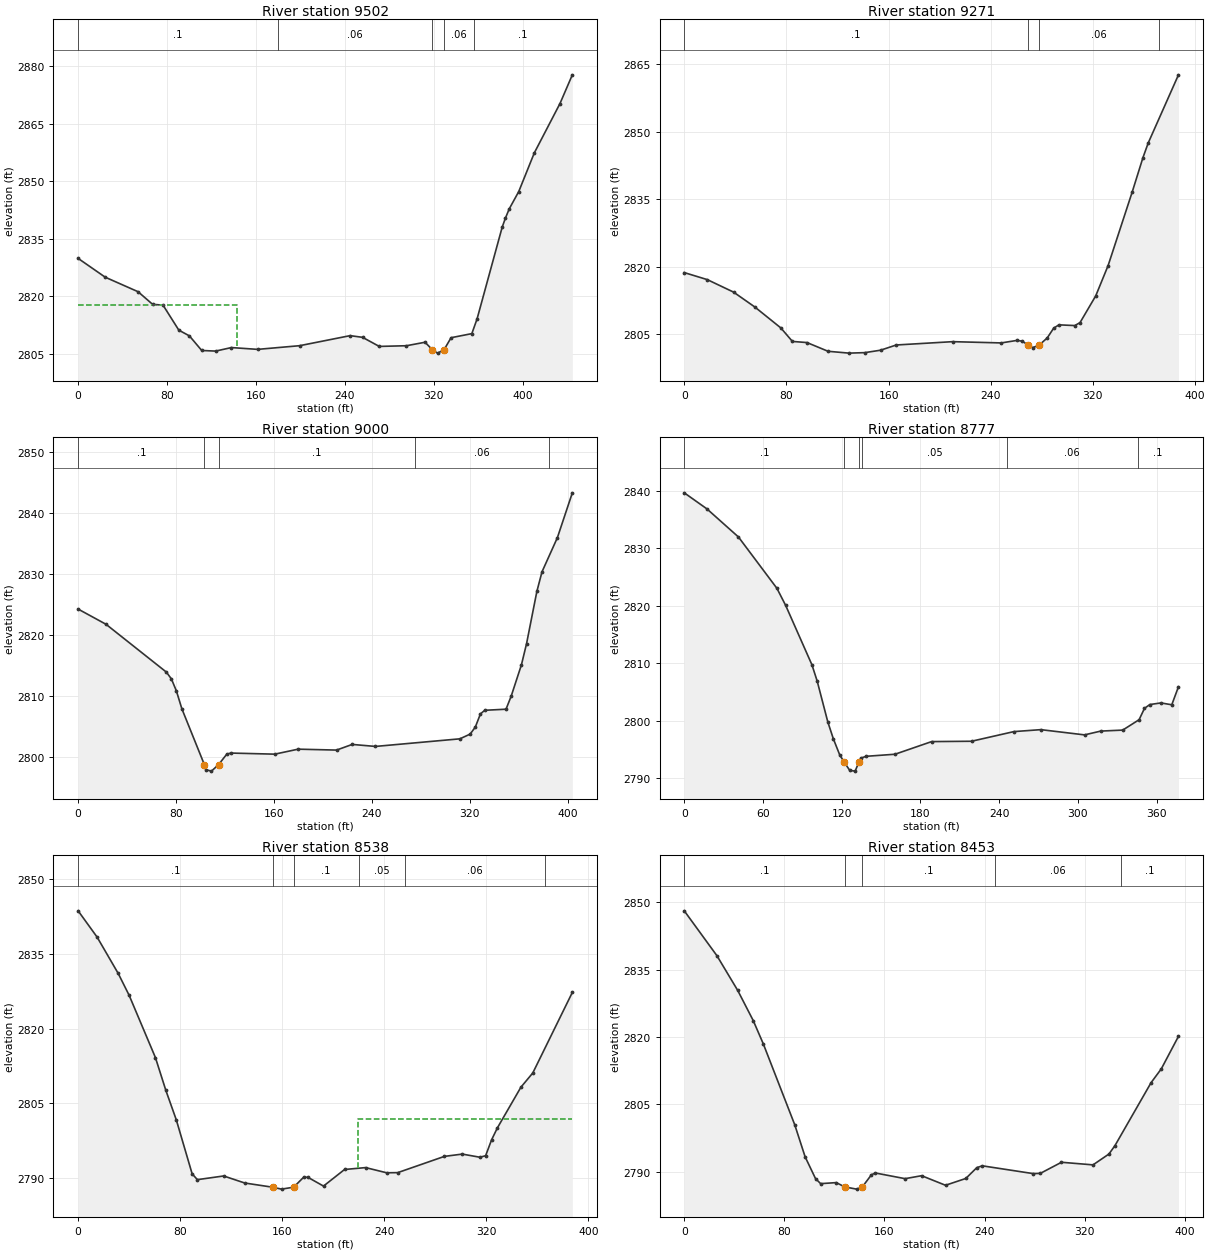
Type RM Length L Ch R = 1 ,9502    ,227.7,230.8,233.9
XS GIS Cut Line= 3
2313288.85563829567640.4843653562313080.61730994567771.548105569
2312910.96627565567874.669322487
#Sta/Elev= 30
       0 2829.92    24.4 2825.01    53.9 2821.23      67 2817.94    76.4 2817.72
    90.6  2811.2   100.1 2809.71   111.2  2805.9   123.7 2805.74   137.9 2806.66
   161.5 2806.19   199.3 2807.15   244.7 2809.77   255.9 2809.33   270.9 2806.96
   295.4 2807.14   312.1 2808.05   318.5 2806.15   323.3 2805.21   329.1 2806.05
   335.5 2809.23   354.2  2810.3   358.9 2814.14   381.5 2838.07   384.4 2840.42
   387.8 2842.82   396.4 2847.36   410.4 2857.44   433.5 2870.32   444.6  2877.8
#Mann= 5 ,-1,0
       0      .1       0     180     .06       0   318.5    .045       0
   329.1     .06       0  356.05      .1       0
#XS Ineff= 2 , 0
          142.86 2817.76
Permanent Ineff=
       F       F
Bank Sta=318.5,329.1
XS Rating Curve= 0 ,0
Exp/Cntr(USF)=0,0
Exp/Cntr=0.3,0.1

Type RM Length L Ch R = 1 ,9271    ,269.7,270.7,266.9
XS GIS Cut Line= 3
 2313197.7097885567569.9627589472313127.85348027567553.330304606
2312821.15102221567625.847805536
#Sta/Elev= 30
       0  2818.7      18 2817.14    38.6 2814.36    55.2 2811.06    75.6  2806.4
    84.7 2803.39    96.1 2803.14   112.6  2801.2     129 2800.79   141.4  2800.9
   153.7 2801.44     166  2802.6   210.2 2803.34   248.2 2803.06   260.6 2803.62
   264.7 2803.45   269.12802.594   272.9 2802.01     2782802.603   284.2 2804.16
   289.3 2806.35   293.4 2807.08   305.8 2806.92   309.9 2807.57   322.2 2813.52
   331.9 2820.26   350.7 2836.56   359.2 2844.28   363.3 2847.52     387 2862.68
#Mann= 4 ,-1,0
       0      .1       0   269.1    .045       0     278     .06       0
  371.81      .1       0
Bank Sta=269.1,278
XS Rating Curve= 0 ,0
Exp/Cntr(USF)=0,0
Exp/Cntr=0.3,0.1

Type RM Length L Ch R = 1 ,9000    ,222.4,223.3,221.5
XS GIS Cut Line= 4
2313198.37508668567409.6258990932313071.96843368567438.899018735
2313006.10391449567475.4904182872312816.49393499567535.367253917
#Sta/Elev= 30
       0 2824.25    22.8 2821.75    72.1 2813.89    76.2 2812.78    80.3  2810.8
    84.8 2807.85   103.22798.663   104.9 2797.81     109 2797.61   114.8 2798.69
   121.5  2800.4   124.8 2800.58   160.7  2800.4   179.8 2801.22   211.2 2801.07
     224    2802     243 2801.67     312 2802.92   320.4  2803.7   324.6 2804.85
   328.8 2807.02   332.3 2807.61   349.7 2807.79   353.9 2809.92   362.3 2815.09
   366.5 2818.58   374.9 2827.14   379.1 2830.37   391.7    2836   403.9 2843.36
#Mann= 5 ,-1,0
       0      .1       0   103.2    .045       0   114.8      .1       0
   275.1     .06       0   385.1      .1       0
Bank Sta=103.2,114.8
XS Rating Curve= 0 ,0
Exp/Cntr(USF)=0,0
Exp/Cntr=0.3,0.1

Type RM Length L Ch R = 1 ,8777    ,235.2,238.5,238.8
XS GIS Cut Line= 3
2313173.42629848567217.7652073322313067.77812114567220.893601455
2312807.28584571567295.279481345
#Sta/Elev= 30
       0 2839.65    17.3 2836.85    41.3 2831.96    70.6 2823.03    77.3 2820.04
    97.3 2809.71   101.3 2806.87   109.4 2799.76   113.6 2796.84   118.5 2794.01
     1222792.736   126.1 2791.34   130.2 2791.21   133.32792.883   134.4 2793.46
   138.6 2793.79   160.6 2794.15   188.5 2796.35   218.9 2796.41   251.2 2798.09
   271.7 2798.43     305 2797.52   317.4 2798.18   334.1 2798.35   346.6 2800.16
   350.7 2802.14   354.8  2802.8   363.2 2803.08   371.5 2802.76   376.6  2805.9
#Mann= 6 ,-1,0
       0      .1       0     122    .045       0   133.3      .1       0
  135.69     .05       0  245.69     .06       0  345.69      .1       0
Bank Sta=122,133.3
XS Rating Curve= 0 ,0
Exp/Cntr(USF)=0,0
Exp/Cntr=0.3,0.1

Type RM Length L Ch R = 1 ,8538    ,83.9,84.9,85
XS GIS Cut Line= 3
2313082.97633183566989.9527230142312843.91582721567049.001240942
 2312721.2324987567118.942203924
#Sta/Elev= 30
       0 2843.64    14.9 2838.36    31.4 2831.09      40 2826.69    60.6  2814.2
    68.8  2807.6      77 2801.68    89.4 2790.87    93.5  2789.7   114.1 2790.44
   130.6 2789.03   152.6 2788.18   159.5  2787.8     169 2788.19   176.8 2790.18
   180.1 2790.18   192.4 2788.41   208.9 2791.74   225.4 2792.12   241.9 2791.08
   250.6 2791.11   287.2 2794.37   301.2 2794.83     315  2794.2   319.5  2794.5
   324.2  2797.7   328.8 2800.12   347.2 2808.26   356.5 2811.11   387.5 2827.27
#Mann= 6 ,-1,0
       0      .1       0   152.6    .045       0     169      .1       0
     220     .05       0  256.25     .06       0  366.25      .1       0
#XS Ineff= 2 , 0
                          219.27         2801.85
Permanent Ineff=
       F       F
Bank Sta=152.6,169
XS Rating Curve= 0 ,0
Exp/Cntr(USF)=0,0
Exp/Cntr=0.3,0.1

Type RM Length L Ch R = 1 ,8453    ,160.4,158.8,156.3
XS GIS Cut Line= 4
2313073.29903003566912.6481633632312920.94574826566954.561948304
2312847.76294915566988.4921551612312699.40145642567037.724220013
#Sta/Elev= 30
       0 2848.09    26.1  2838.1    42.7 2830.38    55.1 2823.67    63.2 2818.45
    88.3 2800.46    96.6 2793.32   104.9 2788.48     109 2787.35   121.5 2787.58
   128.2 2786.63   137.7 2786.13   142.2 2786.58   149.6 2789.33   152.8 2789.72
   176.5 2788.46   189.7 2789.12   208.8 2786.99     225  2788.5   233.8 2790.91
   238.2 2791.32     279 2789.58   284.6 2789.64   301.5 2792.11   326.7 2791.53
   339.4 2793.94   344.2  2795.8   373.1 2809.83   381.3 2812.92     395 2820.15
#Mann= 5 ,-1,0
       0      .1       0   128.2    .045       0   142.2      .1       0
  248.68     .06       0  348.68      .1       0
Bank Sta=128.2,142.2
XS Rating Curve= 0 ,0
Exp/Cntr(USF)=0,0
Exp/Cntr=0.3,0.1

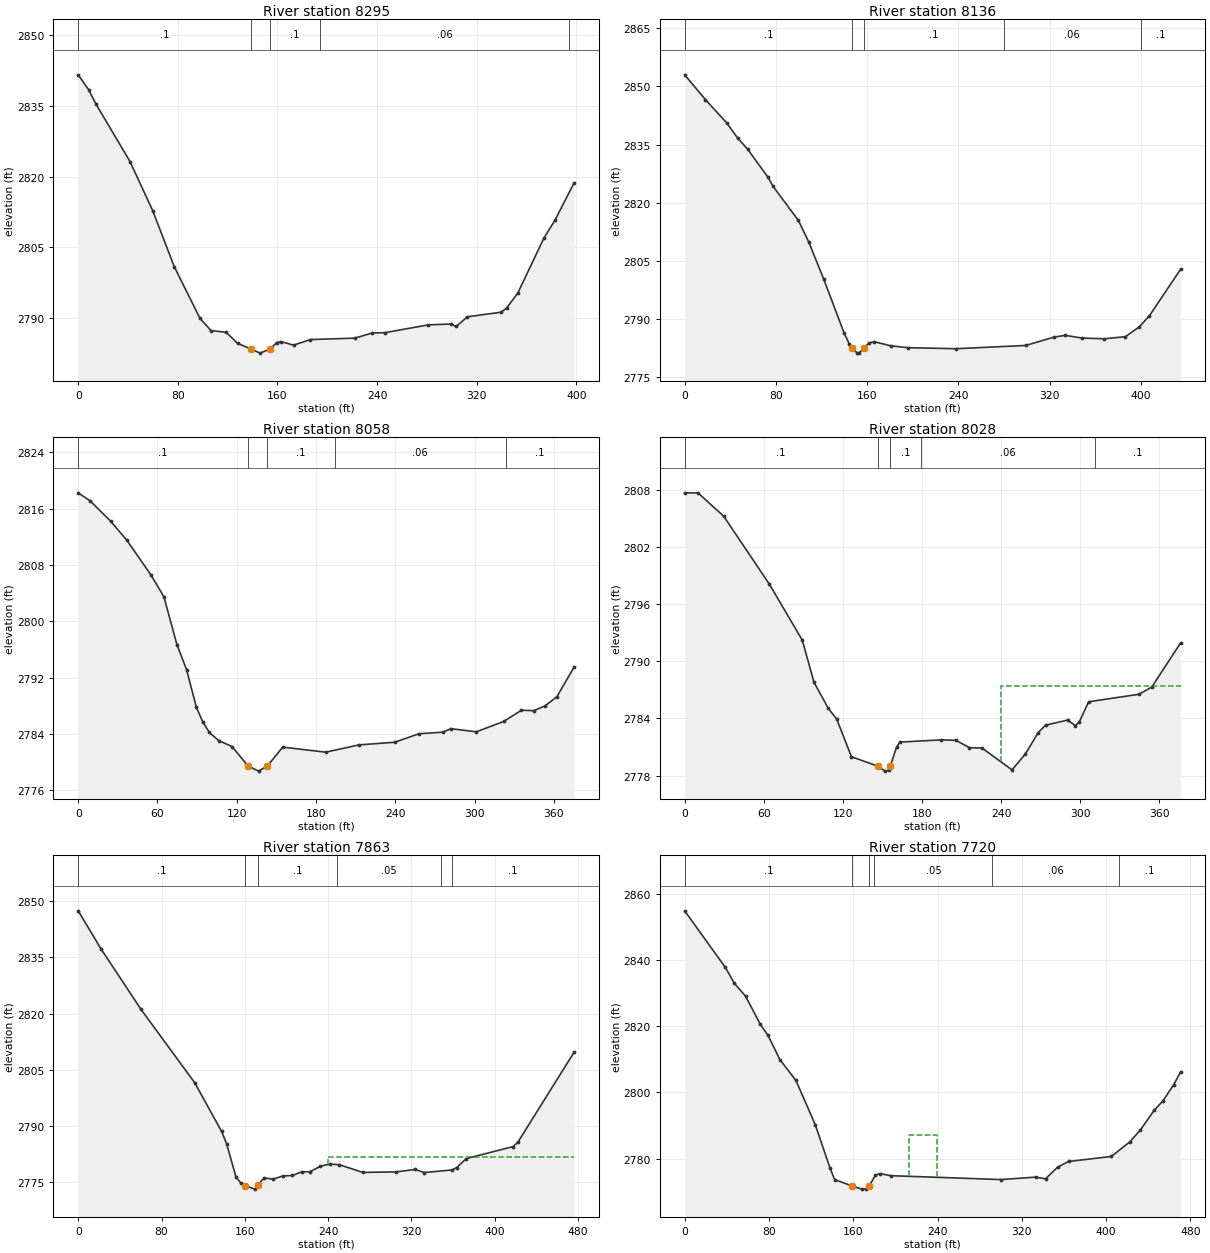
Type RM Length L Ch R = 1 ,8295    ,156,158.8,158.7
XS GIS Cut Line= 3
2312992.77673398566753.2385628962312883.47260136566812.233882649
2312640.02711282566937.957641086
#Sta/Elev= 30
       0 2841.61     8.3 2838.47    14.3 2835.38    41.6 2823.18    59.8 2812.76
    77.2 2800.81    97.8 2789.86   106.7 2787.28   118.9 2786.91   127.9 2784.57
     139 2783.35   145.9 2782.49   154.1 2783.36   159.4 2784.74     163 2784.93
   172.9 2784.18   186.4 2785.37   222.2 2785.68     236 2786.77   246.1 2786.83
     281 2788.49     299 2788.67   303.5 2788.16   312.5 2790.21   339.5 2791.18
   344.1  2792.1     353 2795.28   373.8 2806.86   382.7 2810.69   398.2 2818.68
#Mann= 5 ,-1,0
       0      .1       0     139    .045       0   154.1      .1       0
  194.21     .06       0  394.21      .1       0
Bank Sta=139,154.1
XS Rating Curve= 0 ,0
Exp/Cntr(USF)=0,0
Exp/Cntr=0.3,0.1

Type RM Length L Ch R = 1 ,8136    ,76.9,78,75.6
XS GIS Cut Line= 3
2312982.07789343566609.2904326832312829.01037609566682.671115157
 2312614.0279079566837.458492249
#Sta/Elev= 30
       0 2852.96    18.2 2846.56    36.8 2840.59    46.3  2836.7    55.3 2833.75
    73.1 2826.54    77.5  2824.2    99.7 2815.42   108.6 2809.96   121.9 2800.29
   139.6 2786.52   144.1 2783.71   146.6 2782.58   151.3 2781.23   152.9 2781.31
   157.3  2782.6   161.8 2783.89   166.2 2784.16   180.7 2783.12   195.4 2782.63
   238.1 2782.37   298.9 2783.21     324 2785.37   333.4 2785.81   348.2 2785.12
   367.9 2784.93   386.3 2785.47   398.5 2788.01   407.4 2790.88   434.7 2802.86
#Mann= 5 ,-1,0
       0      .1       0   146.6    .045       0   157.3      .1       0
  279.75     .06       0  399.75      .1       0
Bank Sta=146.6,157.3
XS Rating Curve= 0 ,0
Exp/Cntr(USF)=0,0
Exp/Cntr=0.3,0.1

Type RM Length L Ch R = 1 ,8058    ,33.3,30.1,28.1
XS GIS Cut Line= 4
2312893.21847325566555.974780574 2312759.0694131566650.567066575
2312717.21949263566706.1758650112312606.00189576 566793.88871203
#Sta/Elev= 30
       0 2818.27       9 2817.13    24.6 2814.23    36.8 2811.54    55.1  2806.6
    64.9 2803.49    74.7 2796.72      82 2793.16    89.4 2787.85    94.3 2785.72
    99.3 2784.23   106.2 2783.09   116.4 2782.23   128.5 2779.49   136.5 2778.74
   143.2 2779.47   154.8 2782.15   187.4 2781.43   212.5 2782.47   239.5 2782.84
     258 2784.05   275.8 2784.27   282.2 2784.77   301.3 2784.32   322.1  2785.8
   335.5 2787.39   344.9 2787.33   353.4 2788.01   362.4 2789.32   375.4 2793.54
#Mann= 5 ,-1,0
       0      .1       0   128.5    .045       0   143.2      .1       0
  194.15     .06       0  323.74      .1       0
Bank Sta=128.5,143.2
XS Rating Curve= 0 ,0
Exp/Cntr(USF)=0,0
Exp/Cntr=0.3,0.1

Type RM Length L Ch R = 1 ,8028    ,159.7,165.1,165.3
XS GIS Cut Line= 4
2312875.44989794566519.0384278582312788.45726967566584.585993463
2312730.86615967566643.2309861412312591.66973121566765.224382939
#Sta/Elev= 30
       0 2807.66    10.2 2807.64    29.6 2805.21    64.2 2798.09    89.2 2792.22
    98.1 2787.79   108.9 2785.07   115.4 2783.92   126.5 2779.99   146.42779.006
     152 2778.48   154.8 2778.58     1562779.013   160.7    2781   163.3 2781.52
   194.7 2781.76   205.7 2781.71     216 2780.94   225.6  2780.9   248.3 2778.61
   258.5 2780.29   268.1 2782.51   273.8  2783.3   290.4 2783.83   296.4 2783.25
   299.3 2783.62   306.4 2785.75   344.6 2786.54   354.3 2787.29   376.2 2791.93
#Mann= 5 ,-1,0
       0      .1       0   146.4    .045       0     156      .1       0
  178.92     .06       0  311.12      .1       0
#XS Ineff= 2 , 0
                          239.87         2787.38
Permanent Ineff=
       F       F
Bank Sta=146.4,156
XS Rating Curve= 0 ,0
Exp/Cntr(USF)=0,0
Exp/Cntr=0.3,0.1

Type RM Length L Ch R = 1 ,7863    ,141.3,142.7,143.7
XS GIS Cut Line= 3
2312846.78226012566367.3634951542312739.57766932566455.076342173
2312440.32207361 566611.58357901
#Sta/Elev= 30
       0 2847.43    21.8 2837.32    60.2 2821.19   111.9 2801.58   137.7  2788.6
   142.4 2785.39   151.5 2776.46   155.9 2774.92   160.4 2774.19   169.4 2773.23
   172.2 2774.23   178.5 2776.22   187.1 2775.89   196.5 2776.74   205.6 2776.87
   214.6 2777.84   222.6 2777.88   232.6 2779.34   241.7 2779.91   250.7 2779.74
   273.3 2777.68   305.6 2777.83   323.4 2778.48   332.3 2777.64     359 2778.35
   363.5 2778.99   372.6 2781.37   417.7 2784.58   422.2 2785.76   476.2 2809.76
#Mann= 6 ,-1,0
       0      .1       0   160.4    .045       0   172.2      .1       0
  248.51     .05       0  348.51     .06       0  358.51      .1       0
#XS Ineff= 2 , 0
                          239.69         2781.76
Permanent Ineff=
       F       F
Bank Sta=160.4,172.2
XS Rating Curve= 0 ,0
Exp/Cntr(USF)=0,0
Exp/Cntr=0.3,0.1

Type RM Length L Ch R = 1 ,7720    ,163,163.5,161.6
XS GIS Cut Line= 3
2312811.90457985566275.3239315582312615.52301261 566355.42129542
2312394.65434987 566489.93074764
#Sta/Elev= 30
       0  2854.9    38.6 2837.78    47.2 2832.97    57.9 2829.02    71.8 2820.58
    79.1 2817.24    90.4 2809.89   105.6  2803.6     124 2790.16   137.9 2777.16
   142.3 2773.64   159.1 2771.66   168.2 2770.74   172.5  2770.8   174.92771.562
   181.1 2774.99   185.5 2775.44   195.6 2774.81   300.1 2773.63   333.1 2774.37
   342.5 2773.86   353.9 2777.36   364.3  2779.1     405 2780.62   422.5 2785.04
   432.5 2788.63   445.5 2794.53   453.9 2797.41   464.2 2802.36   470.7 2806.21
#Mann= 6 ,-1,0
       0      .1       0   159.1    .045       0   174.9      .1       0
     180     .05       0  292.09     .06       0  412.09      .1       0
#XS Ineff= 1 ,-1
  212.62   239.22787.073
Permanent Ineff=
       F
Bank Sta=159.1,174.9
XS Rating Curve= 0 ,0
Exp/Cntr(USF)=0,0
Exp/Cntr=0.3,0.1