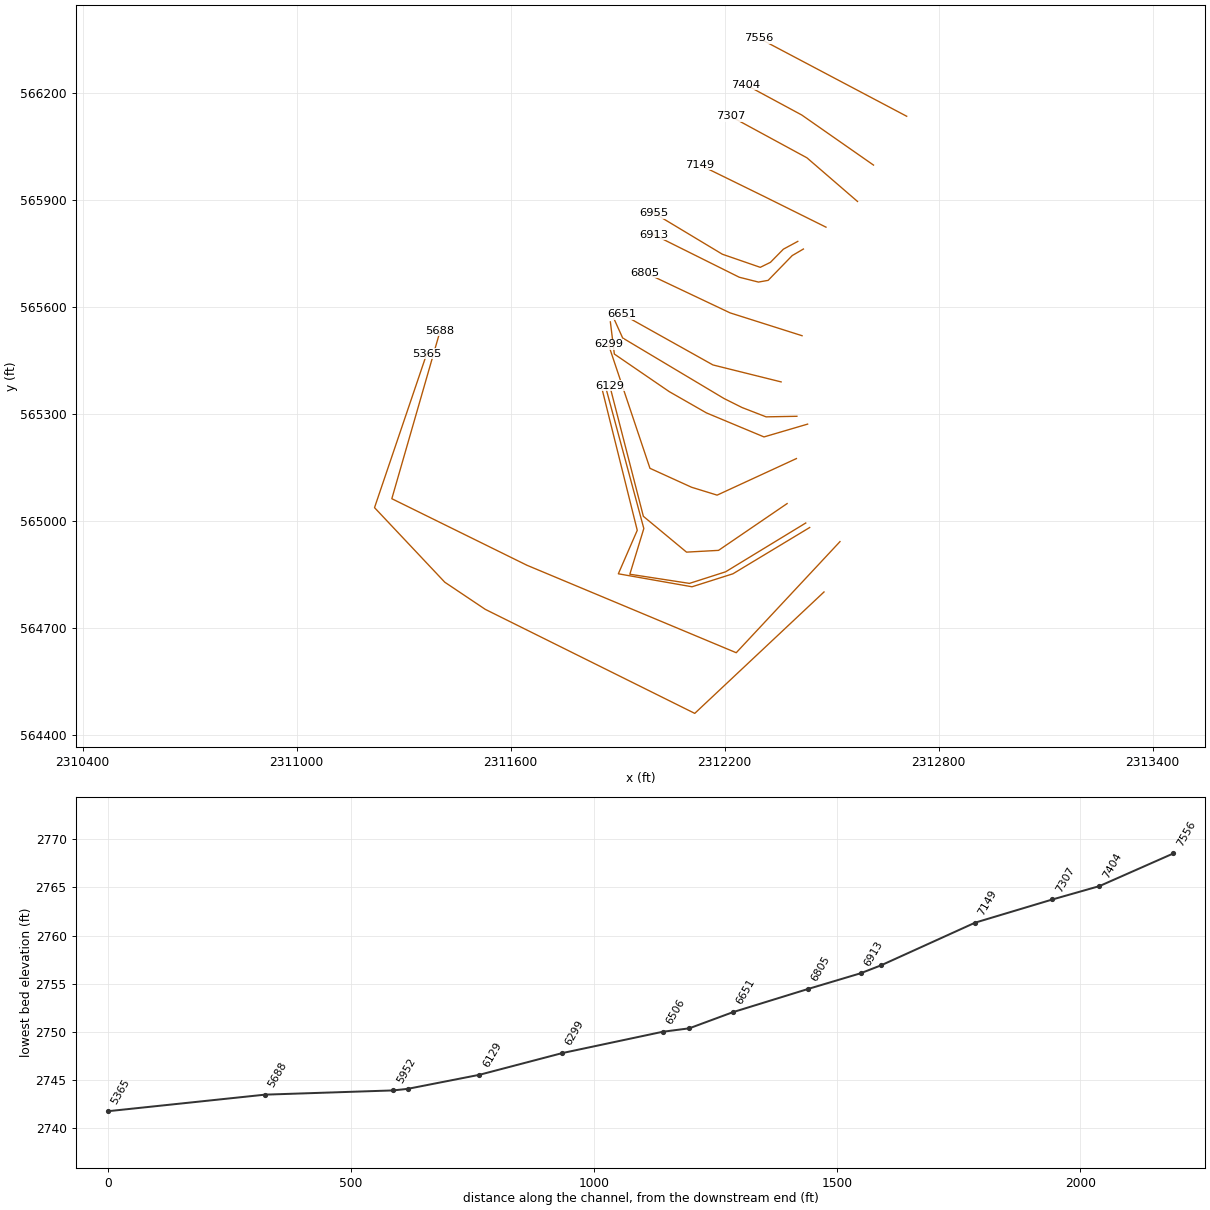
HEC-RAS study JHNSRN.prj: JHNSRN

--- JHNSRN.g01 (geometry) --- (continued)

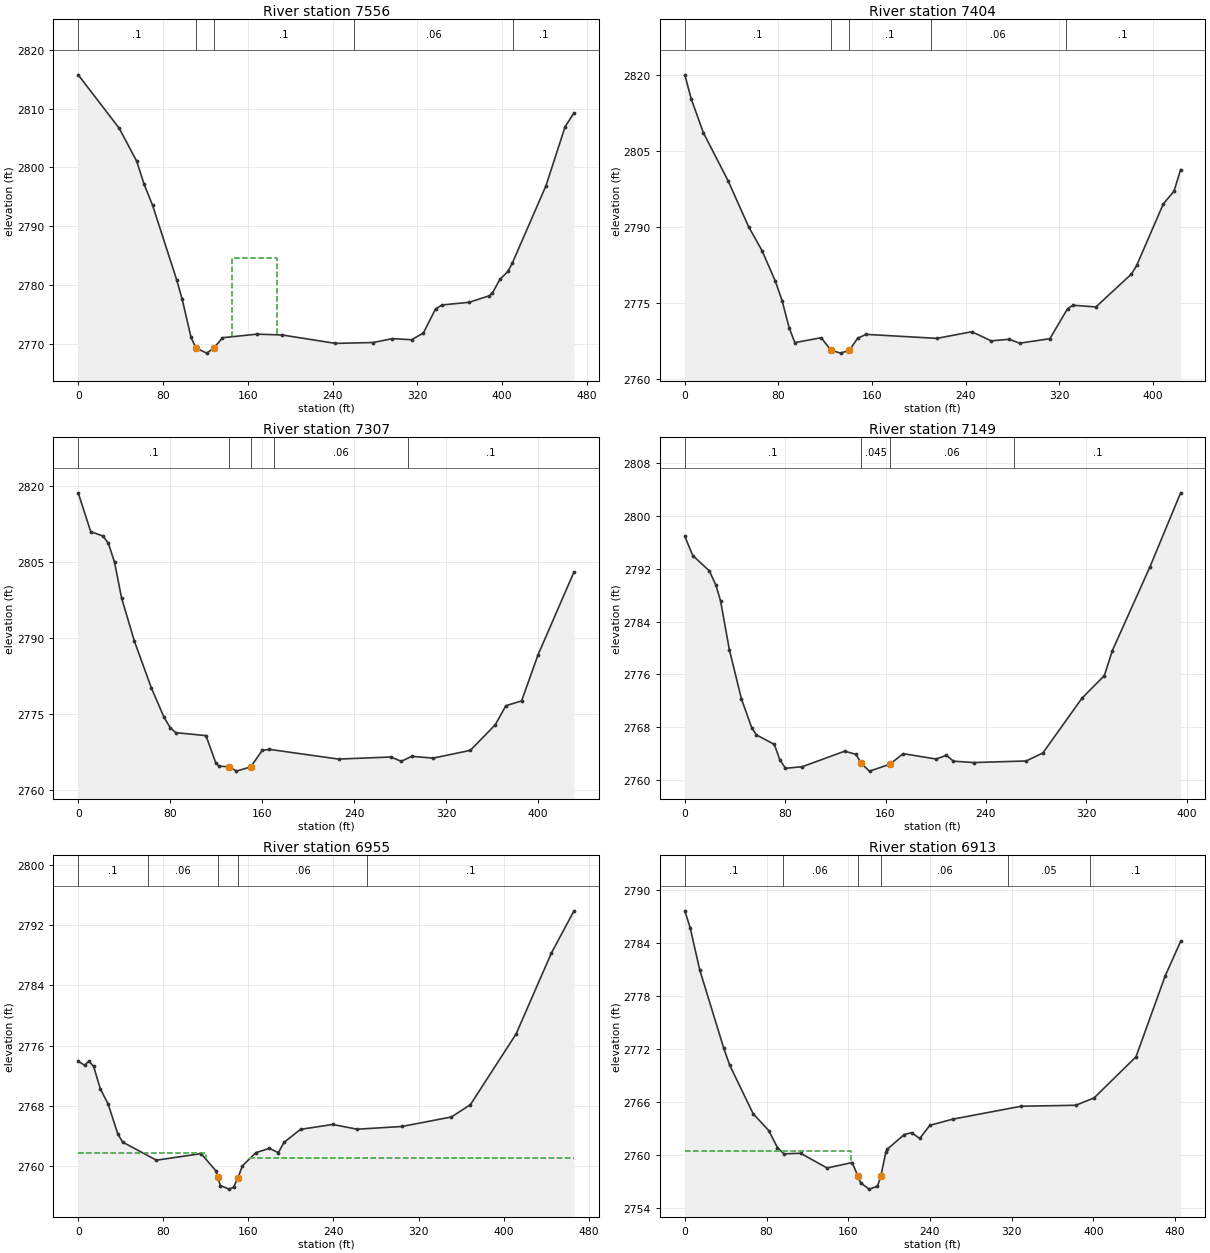
Type RM Length L Ch R = 1 ,7556    ,154.1,152.2,150.1
XS GIS Cut Line= 2
2312710.28825796566135.3783502462312296.69940149566353.823168804
#Sta/Elev= 30
       0 2815.71    38.6 2806.67    55.2 2801.06    62.1 2797.19    70.2 2793.57
    92.9 2780.94    98.1 2777.65   106.4 2771.22     111 2769.39   121.3 2768.52
  128.07 2769.39   136.1 2771.13   168.7 2771.74   192.3  2771.6   242.7 2770.17
   278.3 2770.32   296.4 2770.98   314.5 2770.79   325.6 2771.93   337.1 2776.02
   343.3 2776.69   368.8 2777.14   387.7 2778.24   390.7  2778.7   397.8 2781.02
   405.5  2782.4   409.5 2783.78   441.2 2796.87   459.3 2806.91   467.7 2809.26
#Mann= 5 ,-1,0
       0      .1       0     111    .045       0  128.07      .1       0
     260     .06       0     410      .1       0
#XS Ineff= 1 ,-1
  145.35  187.71 2784.73
Permanent Ineff=
       F
Bank Sta=111,128.07
XS Rating Curve= 0 ,0
Exp/Cntr(USF)=0,0
Exp/Cntr=0.3,0.1

Type RM Length L Ch R = 1 ,7404    ,99.1,96.8,95.5
XS GIS Cut Line= 3
2312617.24326237565998.5270370812312416.01109873566138.978873745
2312259.13214666 566223.57851805
#Sta/Elev= 30
       0 2819.99     5.5 2815.22    15.9 2808.55    37.1 2799.04    54.4 2790.09
    65.9 2785.36    77.4 2779.27    83.1 2775.48    89.1 2770.14      94  2767.2
   116.5 2768.17   124.72765.747     133 2765.13   140.6 2765.69   147.6 2768.06
   154.9 2768.83   215.3 2768.04   245.2 2769.35   261.7 2767.55     277 2767.86
   286.1 2767.09   311.9 2767.98     327 2773.89   331.6 2774.57   351.2 2774.24
   381.6 2780.72   386.1 2782.44   408.8 2794.55   417.9 2797.03   423.6 2801.31
#Mann= 5 ,-1,0
       0      .1       0   124.7    .045       0   140.6      .1       0
     210     .06       0   325.4      .1       0
Bank Sta=124.7,140.6
XS Rating Curve= 0 ,0
Exp/Cntr(USF)=0,0
Exp/Cntr=0.3,0.1

Type RM Length L Ch R = 1 ,7307    ,153,158.7,162.1
XS GIS Cut Line= 3
 2312572.4253058565896.545348623 2312430.6788902566018.874447015
2312216.11753509566135.378350246
#Sta/Elev= 30
       0  2818.7    10.9 2811.02    21.5 2810.18    26.2 2808.76    31.6 2805.01
    37.7 2797.97    48.8 2789.47    63.7 2780.15    74.4 2774.52      80 2772.32
    84.9 2771.34   111.2 2770.75   119.7 2765.37   122.6 2764.71   131.1 2764.62
   137.7 2763.74  150.07 2764.58   160.1 2767.82   166.3 2768.04   226.5 2766.12
     272 2766.53   281.1 2765.68   290.2 2766.66   308.8 2766.31   341.2 2767.84
     363 2772.93   372.1 2776.65   385.8 2777.61   400.2 2786.76   431.4 2803.08
#Mann= 5 ,-1,0
       0      .1       0   131.1    .045       0  150.07      .1       0
     170     .06       0  287.23      .1       0
Bank Sta=131.1,150.07
XS Rating Curve= 0 ,0
Exp/Cntr(USF)=0,0
Exp/Cntr=0.3,0.1

Type RM Length L Ch R = 1 ,7149    ,186.8,193.2,194.6
BEGIN DESCRIPTION:
structure xs 4
END DESCRIPTION:
XS GIS Cut Line= 3
2312484.00737809565824.5091824152312311.56209147565910.133057367
2312129.53651116565999.349542456
#Sta/Elev= 30
       0 2796.92     6.3 2794.02    19.5  2791.7    24.8 2789.52    28.5 2787.13
    35.5 2779.74    45.1  2772.3    53.4 2767.88    57.1 2766.83    71.3 2765.39
    75.7 2763.08    80.2 2761.77    93.6 2762.01   127.4 2764.36   136.4 2763.89
   140.6  2762.5   147.2 2761.34   163.4 2762.38     174 2763.99   200.3 2763.17
   208.5 2763.74   214.1 2762.85   230.2 2762.64   272.1 2762.88   285.4 2764.09
   316.6 2772.41   334.4 2775.82   340.8 2779.62   370.7 2792.28   395.2 2803.52
#Mann= 4 ,-1,0
       0      .1       0   140.6    .045       0   163.4     .06       0
  262.53      .1       0
Bank Sta=140.6,163.4
XS Rating Curve= 0 ,0
Exp/Cntr(USF)=0,0
Exp/Cntr=0.5,0.3

Type RM Length L Ch R = 1 ,6955    ,44.3,42.3,43.4
BEGIN DESCRIPTION:
structure xs 3
END DESCRIPTION:
XS GIS Cut Line= 6
2312404.95729278565784.5827501892312364.63555654565762.797931102
2312328.35961038565725.8855648342312299.83410845565711.889455421
2312193.64876426565748.5841145812312001.44412189565864.146407348
#Sta/Elev= 30
       0 2773.94       6 2773.39      10 2773.96    14.5 2773.24    20.8 2770.26
    28.2 2768.21    37.3 2764.23    41.8 2763.17    73.5 2760.77   115.5 2761.64
   129.5 2759.35   131.22758.519   133.6  2757.4   141.8 2756.92     146 2757.16
   150.2 2758.44   154.4 2760.02     167 2761.77   179.7 2762.34   188.2 2761.77
   193.4 2763.13     209 2764.87   239.2 2765.52   262.2 2764.89   304.3 2765.25
   350.9 2766.52   368.7 2768.15   411.6 2777.54   444.8  2788.3   466.1 2793.93
#Mann= 5 ,-1,0
       0      .1       0   65.83     .06       0   131.2    .045       0
   150.2     .06       0  271.86      .1       0
#XS Ineff= 2 , 0
           120.2 2761.77   161.2            2761
Permanent Ineff=
       F       F
Bank Sta=131.2,150.2
XS Rating Curve= 0 ,0
Exp/Cntr(USF)=0,0
Exp/Cntr=0.5,0.3

Type RM Length L Ch R = 1 ,6913    ,108.3,108.2,108.1
BEGIN DESCRIPTION:
structure xs 2
END DESCRIPTION:
XS GIS Cut Line= 6
2312420.76282504565763.2532433272312389.42328928565744.847104055
2312321.93610783565675.3899747242312294.77597519565670.539951038
2312240.94071228565684.1200173592312000.37953745565803.915602405
#Sta/Elev= 30
       0 2787.68     5.3 2785.72    14.6 2780.97    38.1 2772.09    43.9 2770.17
    66.9 2764.65    82.3 2762.72    90.7  2760.8      97  2760.1   113.4 2760.16
   139.3 2758.49   163.9 2759.11   169.42757.581   172.1 2756.81   180.4 2756.09
   188.6  2756.4   191.9 2757.56   196.9 2760.32   198.4 2760.64   214.9 2762.29
     222  2762.5     230 2761.84   239.9 2763.33   262.3 2764.03   329.3  2765.5
   382.9 2765.61   400.8 2766.45   441.8 2771.11   470.3 2780.27   485.5 2784.22
#Mann= 6 ,-1,0
       0      .1       0   95.81     .06       0   169.4    .045       0
   191.9     .06       0  316.71     .05       0  396.71      .1       0
#XS Ineff= 2 , 0
           162.4  2760.4   198.9          2759.8
Permanent Ineff=
       F       F
Bank Sta=169.4,191.9
XS Rating Curve= 0 ,0
Exp/Cntr(USF)=0,0
Exp/Cntr=0.5,0.3

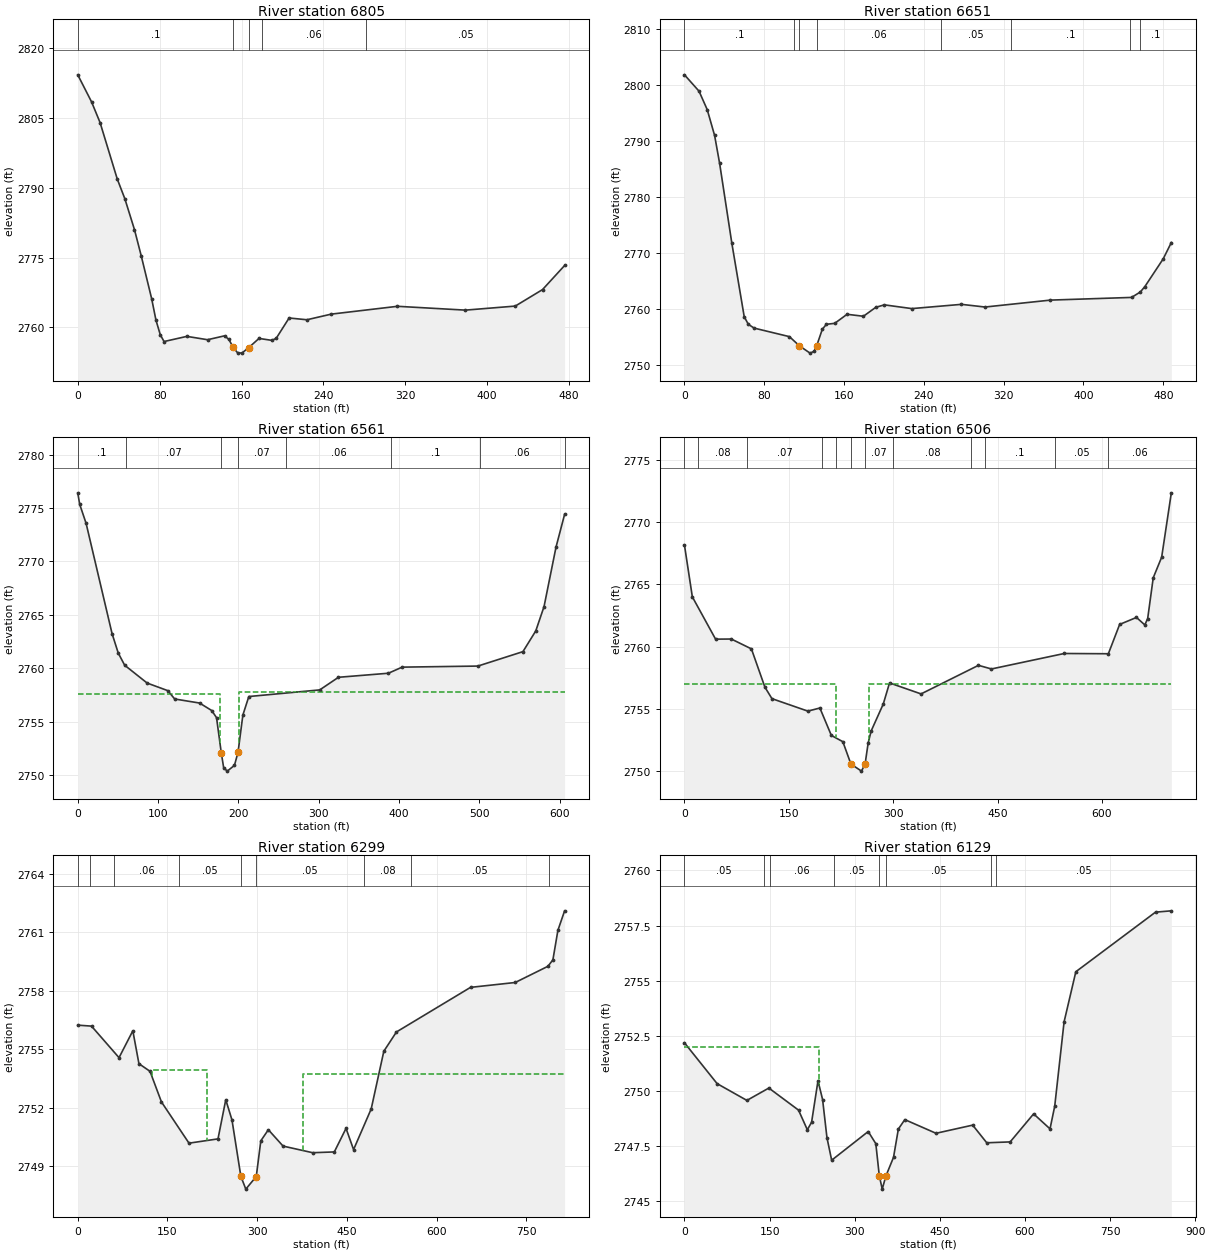
Type RM Length L Ch R = 1 ,6805    ,152.8,154.2,154.5
BEGIN DESCRIPTION:
structure xs 1
END DESCRIPTION:
XS GIS Cut Line= 3
2312416.99657208565520.1892167712312215.23558674565584.209529427
2311976.61442139565697.215081311
#Sta/Elev= 30
       0 2814.26    13.5 2808.44    21.8    2804    38.6 2791.87      46 2787.64
    55.4 2781.01      62 2775.38    72.2 2766.16    76.4 2761.56    80.6 2758.43
    84.3 2756.95   106.6 2758.06   126.8 2757.34   143.5 2758.18   147.7 2757.39
   151.9 2755.67   156.1 2754.55   160.3 2754.46   167.1 2755.65   177.1 2757.62
   189.7  2757.2   193.9 2757.64   206.5 2762.01   223.9 2761.63   247.7 2762.84
   312.4 2764.52   378.8  2763.7   427.5 2764.57   454.1 2768.11   475.7 2773.29
#Mann= 5 ,-1,0
       0      .1       0   151.9    .045       0   167.1      .1       0
     180     .06       0  281.67     .05       0
Bank Sta=151.9,167.1
XS Rating Curve= 0 ,0
Exp/Cntr(USF)=0,0
Exp/Cntr=0.3,0.1

Type RM Length L Ch R = 1 ,6651    ,93.3,90,86.3
BEGIN DESCRIPTION:
structure xs 4
END DESCRIPTION:
XS GIS Cut Line= 3
2312358.31128548565390.6935843532312167.22035225565438.223816476
 2311913.0791111565580.329510478
#Sta/Elev= 30
       0 2801.87    14.6 2798.94    22.8 2795.64    30.2 2791.02    35.2 2786.06
    47.5  2771.7    59.9 2758.57      64 2757.22    69.8 2756.54   105.2 2755.01
   115.2 2753.37   125.9 2752.06     130 2752.39   132.5 2753.35   138.2 2756.34
   142.3 2757.22   150.6 2757.39     163 2759.01   179.4 2758.66   191.8 2760.26
   200.4  2760.7   227.9 2760.03   277.7 2760.79   301.3 2760.31   366.9 2761.55
   448.2 2762.03     457    2763   461.6 2763.98     480 2768.95   488.1 2771.86
#Mann= 8 ,-1,0
       0      .1       0     110     .06       0   115.2    .045       0
   132.5     .06       0  256.91     .05       0  326.91      .1       0
  446.91     .06       0  456.91      .1       0
Bank Sta=115.2,132.5
XS Rating Curve= 0 ,0
Exp/Cntr(USF)=0,0
Exp/Cntr=0.5,0.3

Type RM Length L Ch R = 1 ,6561    ,53.8,54.8,55.8
BEGIN DESCRIPTION:
structure xs 3
END DESCRIPTION:
XS GIS Cut Line= 6
2312402.55082043565294.3095281992312316.11607941565292.723105895
2312248.70075017  565318.91323382312198.26050384565344.133356967
2311914.04911584565513.8841859792311889.38454952565568.472447666
#Sta/Elev= 30
       0 2776.42     2.4 2775.35    10.4 2773.56    42.7 2763.25    50.4 2761.43
    58.4 2760.29    86.4 2758.62   112.1 2757.91   120.7 2757.13   151.7 2756.75
   166.8 2756.05   172.8 2755.38   178.7 2752.09   181.7 2750.69   186.2 2750.38
   195.1 2750.92   199.6 2752.15   199.6 2752.16   205.6 2755.63     213 2757.36
   301.3 2757.98   324.6 2759.16   386.8 2759.54   403.9 2760.11   498.2 2760.21
   554.3 2761.56   570.3  2763.5   580.6 2765.78   595.5 2771.34   606.2 2774.41
#Mann= 8 ,-1,0
       0      .1       0      60     .07       0   178.7    .045       0
   199.6     .07       0   258.8     .06       0  390.33      .1       0
  500.33     .06       0  606.18      .1       0
#XS Ineff= 2 , 0
          177.53 2757.55   201.1         2757.74
Permanent Ineff=
       F       F
Bank Sta=178.7,199.6
XS Rating Curve= 0 ,0
Exp/Cntr=0.5,0.3

Type RM Length L Ch R = 1 ,6506    ,205.1,206.5,208
BEGIN DESCRIPTION:
structure xs 2
END DESCRIPTION:
XS GIS Cut Line= 6
2312432.51664788565272.3530064132312310.29605099565236.462831137
2312148.79026224565303.8781603732312044.51475299565363.533451711
2311890.76900214565468.7789656982311879.61394767565558.989406259
#Sta/Elev= 30
       0 2768.13    11.3 2763.99    44.7  2760.6    67.3 2760.61    96.2 2759.82
   115.6 2756.75   125.7 2755.83   177.3 2754.83   194.6 2755.08   211.1 2752.88
   227.6 2752.38   239.22750.588   254.4 2750.02   259.6  2750.6     264 2752.28
   268.3 2753.24   285.7  2755.4   294.7 2757.09     340 2756.21   422.5  2758.5
   441.2 2758.21   545.8 2759.45   609.2 2759.43   625.4 2761.78   649.6 2762.34
   661.6 2761.74   665.7 2762.25   673.7 2765.52   685.8 2767.17   699.7 2772.33
#Mann= 12 ,-1,0
       0      .1       0      20     .08       0      90     .07       0
  197.38     .05       0  217.38     .07       0   239.2    .045       0
   259.6     .07       0  300.24     .08       0  412.39     .06       0
  432.53      .1       0  532.53     .05       0  608.85     .06       0
#XS Ineff= 2 , 0
          217.94 2757.02   264.6            2757
Permanent Ineff=
       F       F
Bank Sta=239.2,259.6
XS Rating Curve= 0 ,0
Exp/Cntr(USF)=0,0
Exp/Cntr=0.5,0.3

Type RM Length L Ch R = 1 ,6299    ,175.2,170.2,165.7
BEGIN DESCRIPTION:
strucure xs 1
END DESCRIPTION:
XS GIS Cut Line= 5
2312401.10259871565175.7583645782312178.89300871565073.302445833
2312107.42452744565095.3154833992311990.61362555565148.481139459
2311874.18644516565495.766786113
#Sta/Elev= 30
       0 2756.23      23 2756.18      69 2754.56    92.1 2755.94   102.3 2754.25
   120.8 2753.86   139.9 2752.29     186 2750.17   234.5 2750.39   247.5  2752.4
   257.9 2751.36   272.7 2748.47     281 2747.81   298.52748.458   306.1 2750.29
   318.7 2750.86   343.3 2750.02   392.8 2749.68     429 2749.72   448.6 2750.93
   461.2 2749.84   490.7 2751.93   511.8 2754.89   532.9 2755.88   656.8 2758.17
   731.5 2758.42   786.1 2759.25   794.5 2759.58   802.9  2761.1   814.1  2762.1
#Mann= 9 ,-1,0
       0     .08       0      20     .05       0      60     .06       0
     170     .05       0   272.7    .045       0   298.5     .05       0
  477.81     .08       0  557.81     .05       0  787.81     .06       0
#XS Ineff= 2 ,-1
  124.58  215.95 2753.95  377.04   814.12753.728
Permanent Ineff=
       F       F
Bank Sta=272.7,298.5
XS Rating Curve= 0 ,0
Exp/Cntr(USF)=0,0
Exp/Cntr=0.3,0.1

Type RM Length L Ch R = 1 ,6129    ,163.7,147.7,132.7
BEGIN DESCRIPTION:
xs 4
END DESCRIPTION:
XS GIS Cut Line= 5
2312375.04239371565049.5820369852312182.84500552564918.443945823
2312093.11510854 564913.517271282311972.09301997565013.912606805
 2311877.8563979565380.248888275
#Sta/Elev= 30
       0 2752.19    57.5 2750.34     110 2749.58   148.7 2750.14     201 2749.14
   216.5 2748.25     224 2748.59   235.3 2750.47   243.4 2749.62   251.1 2747.89
   259.4 2746.87   323.8 2748.17   337.2 2747.62   343.32746.173   348.5 2745.56
   354.9 2746.15   368.4    2747   376.9 2748.28   388.3 2748.71   443.3 2748.09
   507.9 2748.46   532.7 2747.66     574  2747.7   615.3 2748.97   644.2 2748.29
   652.5 2749.32     669 2753.14   689.7 2755.41   830.1 2758.11     858 2758.17
#Mann= 8 ,-1,0
       0     .05       0     140     .07       0     150     .06       0
  262.67     .05       0   343.3    .045       0   354.9     .05       0
  539.78     .08       0  549.78     .05       0
#XS Ineff= 2 , 0
          237.75 2751.98
Permanent Ineff=
       F       F
Bank Sta=343.3,354.9
XS Rating Curve= 0 ,0
Exp/Cntr(USF)=0,0
Exp/Cntr=0.5,0.3

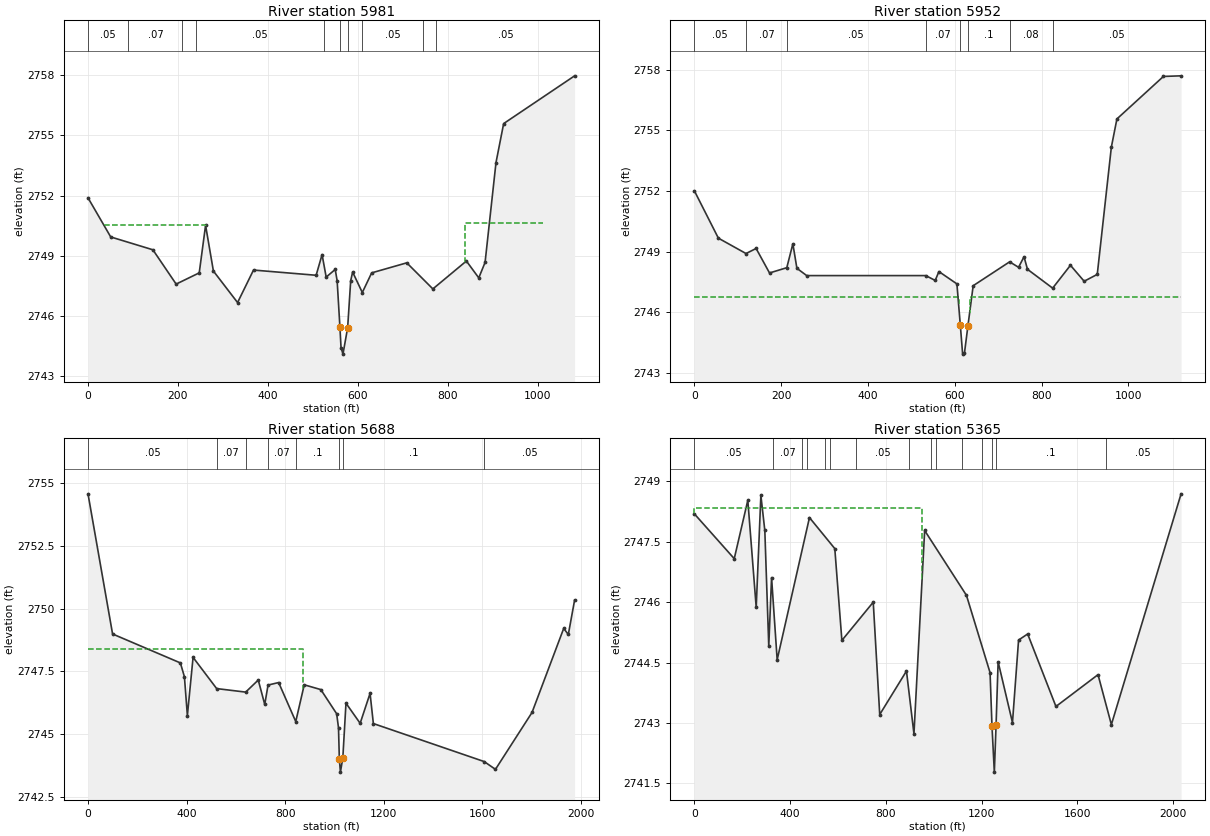
Type RM Length L Ch R = 1 ,5981    ,29.7,29.4,28.9
BEGIN DESCRIPTION:
xs 3
END DESCRIPTION:
XS GIS Cut Line= 6
2312427.32289797564995.1894330952312202.62477028564858.313460951
2312101.35237471564825.8746467432311934.21210431564851.522827772
2311973.41005329564979.6906707532311867.15995994 565373.37853532
#Sta/Elev= 30
       0 2751.89    50.5 2749.94   144.2  2749.3   195.9 2747.59   247.2 2748.15
   261.3 2750.52   278.7 2748.24   332.4 2746.67   367.8 2748.29     507 2748.03
   520.2 2749.06   529.3 2747.94   549.4 2748.32   553.7 2747.75   559.8 2745.46
   562.3 2744.43   566.6  2744.1     5772745.414   583.8 2747.76   588.1 2748.19
   609.6 2747.17   630.4 2748.15   708.4 2748.65   766.4 2747.35   840.9 2748.74
   868.4  2747.9   882.4 2748.67   906.7 2753.65   923.7 2755.59  1081.4 2757.97
#Mann= 10 ,-1,0
       0     .05       0      90     .07       0     210     .06       0
     240     .05       0     524     .07       0   559.8    .045       0
     577      .1       0  609.07     .05       0  743.67     .08       0
  773.67     .05       0
#XS Ineff= 4 ,-1
   35.15  262.31 2750.56  262.31   549.8 2747.83   586.9  711.21  2747.8
  836.79 1010.032750.636
Permanent Ineff=
       F       F       F       F
Bank Sta=559.8,577
XS Rating Curve= 0 ,0
Exp/Cntr(USF)=0,0
Exp/Cntr=0.5,0.3

Type RM Length L Ch R = 1 ,5952    ,242.3,263.8,282.2
BEGIN DESCRIPTION:
xs 2
END DESCRIPTION:
XS GIS Cut Line= 6
2312438.39956623564982.5303836482312223.19572564564852.775126818
2312108.47309002564816.3803596582311901.97234592564852.775126818
2311954.98211548564974.6184777442311856.87448227565368.631391778
#Sta/Elev= 30
       0    2752    55.1 2749.67   118.8 2748.91   142.1 2749.16     173 2747.95
   212.8 2748.21   226.8 2749.39   236.1 2748.18   258.7 2747.82   533.2 2747.82
   554.9 2747.58   563.4 2748.02   604.9 2747.41   612.72745.391   618.1 2743.94
   622.3 2743.99   630.2 2745.32   642.4 2747.32   726.4  2748.5     747 2748.23
   759.6 2748.75   767.6 2748.13   825.6  2747.2   866.6 2748.33   898.2 2747.54
   928.4 2747.88   960.9 2754.17   973.7 2755.56  1080.9 2757.66  1121.6 2757.69
#Mann= 8 ,-1,0
       0     .05       0   118.8     .07       0   212.8     .05       0
   533.2     .07       0   612.7    .045       0   630.2      .1       0
   726.4     .08       0   825.6     .05       0
#XS Ineff= 2 ,-1
       0   608.7 2746.75   634.21121.565 2746.75
Permanent Ineff=
       F       F
Bank Sta=612.7,630.2
XS Rating Curve= 0 ,0
Exp/Cntr(USF)=0,0
Exp/Cntr=0.5,0.3

Type RM Length L Ch R = 1 ,5688    ,323.4,323.4,323.4
XS GIS Cut Line= 5
 2312523.3196043564943.0175224332312232.45667119 564631.53370974
2311645.96006786564876.6334118922311266.98950078565063.293927691
2311402.46559791565533.732698663
#Sta/Elev= 30
       0 2754.56    99.7 2748.99   374.7 2747.84   391.1 2747.29   403.1 2745.75
   426.2 2748.06   521.9 2746.82   639.6 2746.68   690.6 2747.16   716.9 2746.19
   730.3 2746.96   773.3 2747.06   842.7 2745.51   877.1 2746.97   944.4 2746.78
  1008.6 2745.82  1016.1 2745.26  1019.52744.023  1023.9  2743.5  1033.72744.077
  1046.4 2746.24  1103.9 2745.44  1144.1 2746.63  1157.5 2745.43  1606.9 2743.92
  1652.7 2743.61    1801 2745.87  1929.5 2749.21  1948.3 2748.97  1973.8 2750.34
#Mann= 8 ,-1,0
       0     .05       0   521.9     .07       0   639.6     .05       0
   730.3     .07       0   842.7      .1       0  1019.5    .045       0
  1033.7      .1       0  1606.9     .05       0
#XS Ineff= 2 , 0
          873.24 2748.38
Permanent Ineff=
       F       F
Bank Sta=1019.5,1033.7
XS Rating Curve= 0 ,0
Exp/Cntr(USF)=0,0
Exp/Cntr=0.3,0.1

Type RM Length L Ch R = 1 ,5365    ,,,
XS GIS Cut Line= 6
2312478.51746923564801.8542641672312116.16212078 564461.48916106
2311529.08876071564753.0153388322311415.47967844564829.154021912
2311218.47319558565038.2346627892311364.98997159565469.970762752
#Sta/Elev= 30
       0 2748.19   166.3 2747.08     223 2748.53   258.1 2745.87   277.6 2748.65
   294.1 2747.78   310.6 2744.91   322.3 2746.61   345.7 2744.57   480.7  2748.1
   586.6 2747.33   616.2 2745.05   747.3    2746   774.4 2743.21   886.2 2744.29
   917.5 2742.73   962.2 2747.78  1136.9 2746.17  1235.6 2744.25  1243.72742.916
  1253.5 2741.78  1260.7 2742.94  1269.3 2744.52  1329.3 2743.01  1354.8 2745.06
  1392.8 2745.21    1511 2743.41  1686.9  2744.2  1742.7 2742.96  2034.1 2748.69
#Mann= 15 ,-1,0
       0     .05       0     330     .07       0     450     .05       0
     470     .07       0  547.14     .05       0  567.14     .07       0
  677.14     .05       0  897.14     .07       0  987.83     .05       0
 1007.83      .1       0 1117.83     .08       0 1202.62      .1       0
  1243.7    .045       0  1260.7      .1       0  1718.2     .05       0
#XS Ineff= 2 , 0
             951 2748.34
Permanent Ineff=
       F       F
Bank Sta=1243.7,1260.7
XS Rating Curve= 0 ,0
Exp/Cntr(USF)=0,0
Exp/Cntr=0.3,0.1
LCMann Table=0

Chan Stop Cuts=-1
Use User Specified Reach Order=0
Composite Channel Slope=5